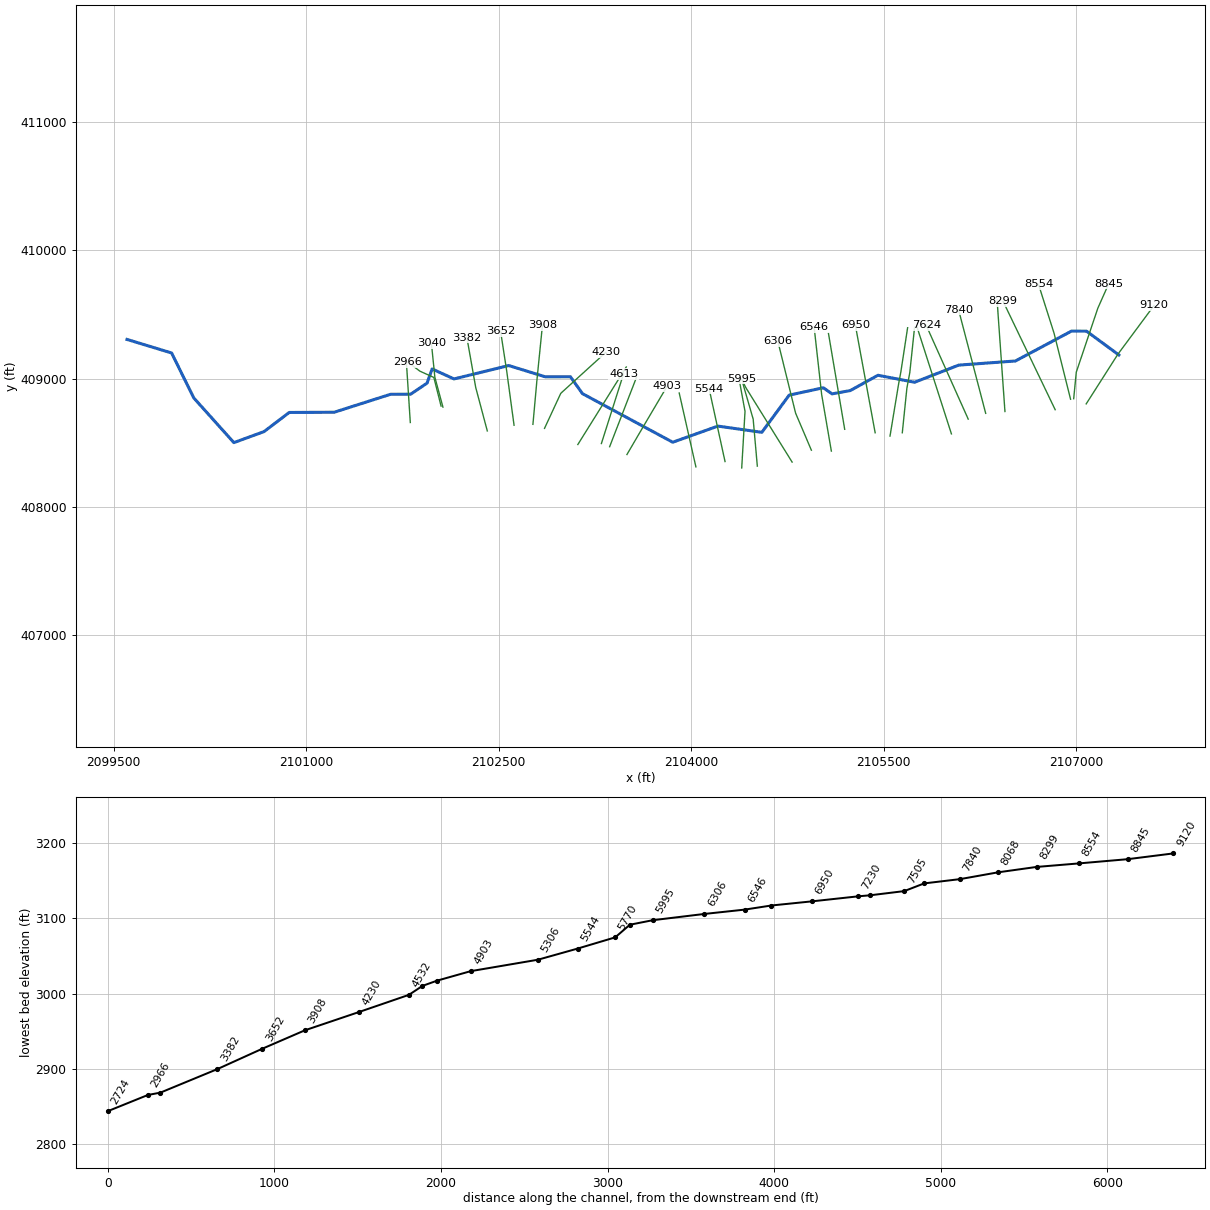
--- MIDDLEBR.prj (project) ---

Proj Title=MIDDLEBR
Current Plan=p01
Default Exp/Contr=0.3,0.1
English Units
Geom File=g01
Flow File=f01
Plan File=p01
Y Axis Title=Elevation
X Axis Title(PF)=Main Channel Distance
X Axis Title(XS)=Station
BEGIN DESCRIPTION:
Stream Name- Middle Branch
Flood Zone: Zone A
Greenbrier County, WV
County-Wide Study
WVDHSEM-2018-3, Flood Risk Project
HEC-RAS Version: 5.0.7
General Notes:
For the Hydrology Regression was used.
END DESCRIPTION:
DSS Export Rating Curves= 0
DSS Export Rating Curve Sorted= 0
DSS Export Volume Flow Curves= 0
DXF Filename=..\M2.
DXF OffsetX= 0
DXF OffsetY= 0
DXF ScaleX= 1
DXF ScaleY= 10

--- MIDDLEBR.p01 (plan) ---

Plan Title=Floodplain
Program Version=5.07
Short Identifier=Floodplain
Geom File=g01
Flow File=f01
Subcritical Flow
K Sum by GR= 0
Std Step Tol= 0.01
Critical Tol= 0.01
Num of Std Step Trials= 20
Max Error Tol= 0.3
Flow Tol Ratio= 0.001
Split Flow NTrial= 30
Split Flow Tol= 0.02
Split Flow Ratio= 0.02
Log Output Level= 0
Friction Slope Method= 1
Unsteady Friction Slope Method= 2
Unsteady Bridges Friction Slope Method= 1
Parabolic Critical Depth
Global Vel Dist= 0 , 0 , 0
Global Log Level= 0
CheckData=True
Encroach Param=-1 ,0,0, 0
Computation Interval=1MIN
Output Interval=1HOUR
Instantaneous Interval=1HOUR
Mapping Interval=1HOUR
Computation Time Step Use Courant=        0
Computation Time Step Use Time Series=    0
Computation Time Step Count To Double=0
Computation Time Step Max Doubling=0
Computation Time Step Max Halving=0
Computation Time Step Residence Courant=0
Run HTab= 0
Run UNet= 0
Run Sediment= 0
Run PostProcess= 0
Run WQNet= 0
Run RASMapper= 0
UNET Theta= 1
UNET Theta Warmup= 1
UNET ZTol= 0.02
UNET ZSATol= 0.02
UNET MxIter= 20
UNET Max Iter WO Improvement= 0
UNET MaxInSteps= 0
UNET DtIC= 0
UNET DtMin= 0
UNET MaxCRTS= 20
UNET WFStab= 2
UNET SFStab= 1
UNET WFX= 1
UNET SFX= 1
UNET 1D Methodology=Finite Difference
UNET DSS MLevel= 4
UNET Pardiso=0
UNET DZMax Abort= 100
UNET Use Existing IB Tables=-1
UNET Froude Reduction=False
UNET Froude Limit= 0.8
UNET Froude Power= 4
UNET D1 Cores= 0
UNET D2 Coriolis=0
UNET D2 Cores= 0
UNET D2 Theta= 1
UNET D2 Theta Warmup= 1
UNET D2 Z Tol= 0.01
UNET D2 Volume Tol= 0.01
UNET D2 Max Iterations= 20
UNET D2 Equation= 0
UNET D2 RampUpFraction=0.1
UNET D2 TimeSlices= 1
UNET D2 BCVolumeCheck=0
UNET D1D2 MaxIter= 0
UNET D1D2 ZTol=0.01
UNET D1D2 QTol=0.1
UNET D1D2 MinQTol=1
Write IC File= 0
Write IC File at Fixed DateTime=0
Write IC File at Sim End=0
Echo Input=False
Echo Parameters=False
Echo Output=False
Write Detailed= 0
HDF Write Warmup=0
HDF Write Time Slices=0
HDF Flush=0
HDF Face Node Velocities=0
HDF Compression= 1
HDF Chunk Size= 1
HDF Spatial Parts= 1
HDF Use Max Rows=0
HDF Fixed Rows= 1
Calibration Method= 0
Calibration Iterations= 20
Calibration Max Change=0.05
Calibration Tolerance=0.2
Calibration Maximum=1.5
Calibration Minimum=0.5
Calibration Optimization Method= 1
WQ AD Non Conservative
WQ ULTIMATE=-1
WQ Max Comp Step=1HOUR
WQ Output Interval=15MIN
WQ Output Selected Increments= 0
WQ Output face flow=0
WQ Output face velocity=0
WQ Output face area=0
WQ Output face dispersion=0
WQ Output cell volume=0
WQ Output cell surface area=0
WQ Output cell continuity=0
WQ Output cumulative cell continuity=0
WQ Output face conc=0
WQ Output face dconc_dx=0
WQ Output face courant=0
WQ Output face peclet=0
WQ Output face adv mass=0
WQ Output face disp mass=0
WQ Output cell mass=0
WQ Output cell source sink temp=0
WQ Output nsm pathways=0
WQ Output nsm derived pathways=0
WQ Output MaxMinRange=-1
WQ Daily Max Min Mean=-1
WQ Daily Range=0
WQ Daily Time=0
WQ Create Restart=0
WQ Fixed Restart=0
WQ System Summary=0
WQ Write To DSS=0
WQ Use Fixed Temperature=0
Sorting and Armoring Iterations= 10
XS Update Threshold= 0.02
Bed Roughness Predictor= 0
Hydraulics Update Threshold= 0.02
Energy Slope Method= 1
Volume Change Method= 1
Sediment Retention Method= 0
XS Weighting Method= 0
Number of US Weighted Cross Sections= 1
Number of DS Weighted Cross Sections= 1
Upstream XS Weight=0
Main XS Weight=1
Downstream XS Weight=0
Number of DS XS's Weighted with US Boundary= 1
Upstream Boundary Weight= 1
Weight of XSs Associated with US Boundary= 0
Number of US XS's Weighted with DS Boundary= 1
Downstream Boundary Weight= 0.5
Weight of XSs Associated with DS Boundary= 0.5
Percentile Method= 0
Sediment Output Level= 3
Mass or Volume Output= 0
Output Increment Type= 1
Profile and TS Output Increment= 1
XS Output Flag= 0
XS Output Increment= 10
Write Gradation File= 0
Read Gradation Hotstart= 0
Write HDF5 File= 1
Write Binary Output= 1
Write DSS Sediment File= 0
SV Curve= 0
Specific Gage Flag= 0

--- MIDDLEBR.f01 (steady flow) ---

Flow Title=Flow
Program Version=5.07
Number of Profiles= 6
Profile Names=f1p,f10p,f4p,f2p,f02p,f1pplus
River Rch & RM=MIDDLEBR,Main            ,9120
     499     262     350     422     699     738
River Rch & RM=MIDDLEBR,Main            ,8068
     567     300     399     480     793     839
River Rch & RM=MIDDLEBR,Main            ,6306
     633     336     445     536     882     936
Boundary for River Rch & Prof#=MIDDLEBR,Main            , 1
Up Type= 0
Dn Type= 3
Dn Slope=0.01996
Boundary for River Rch & Prof#=MIDDLEBR,Main            , 2
Up Type= 0
Dn Type= 3
Dn Slope=0.01996
Boundary for River Rch & Prof#=MIDDLEBR,Main            , 3
Up Type= 0
Dn Type= 3
Dn Slope=0.01996
Boundary for River Rch & Prof#=MIDDLEBR,Main            , 4
Up Type= 0
Dn Type= 3
Dn Slope=0.01996
Boundary for River Rch & Prof#=MIDDLEBR,Main            , 5
Up Type= 0
Dn Type= 3
Dn Slope=0.01996
Boundary for River Rch & Prof#=MIDDLEBR,Main            , 6
Up Type= 0
Dn Type= 3
Dn Slope=0.01996
DSS Import GetInterval= 0
DSS Import GetPeak= 0
DSS Import FillOption= 0

--- MIDDLEBR.g01 (geometry) ---

Geom Title=Geometry
Program Version=5.07

River Reach=MIDDLEBR        ,Main
Reach XY= 30
2107332.92609903409184.8640484662107080.86496501409370.309532953
2106963.30439907409371.0092982272106526.57403719409138.160073623
2106085.13988069409106.047933131 2105740.7291522408972.469132051
2105455.51384336409027.029062301 2105240.1120432408907.720901966
2105097.99913844408881.8909011332105029.55603385408929.638837129
2104763.68812728408871.903060213 2104551.0130277408582.243862629
2104208.88083795408630.817912459 2103856.7109386408505.196116462
2103153.84685877408883.5690473772103059.61769562409015.427187856
 2102863.2900252409014.9969341312102579.10785076409102.683110461
2102152.77405778408998.4608779552101982.10806051 409076.03191705
2101942.37487227408965.5049071312101814.82493052408879.159935459
2101658.42891786 408878.799043792101219.36286685408738.847880125
2100868.96100861408737.1628441212100672.25306869408587.808155954
2100437.52814445408502.1790621282100125.18296862408850.247919798
2099952.43889153409200.5959723742099605.04194853409306.125945047

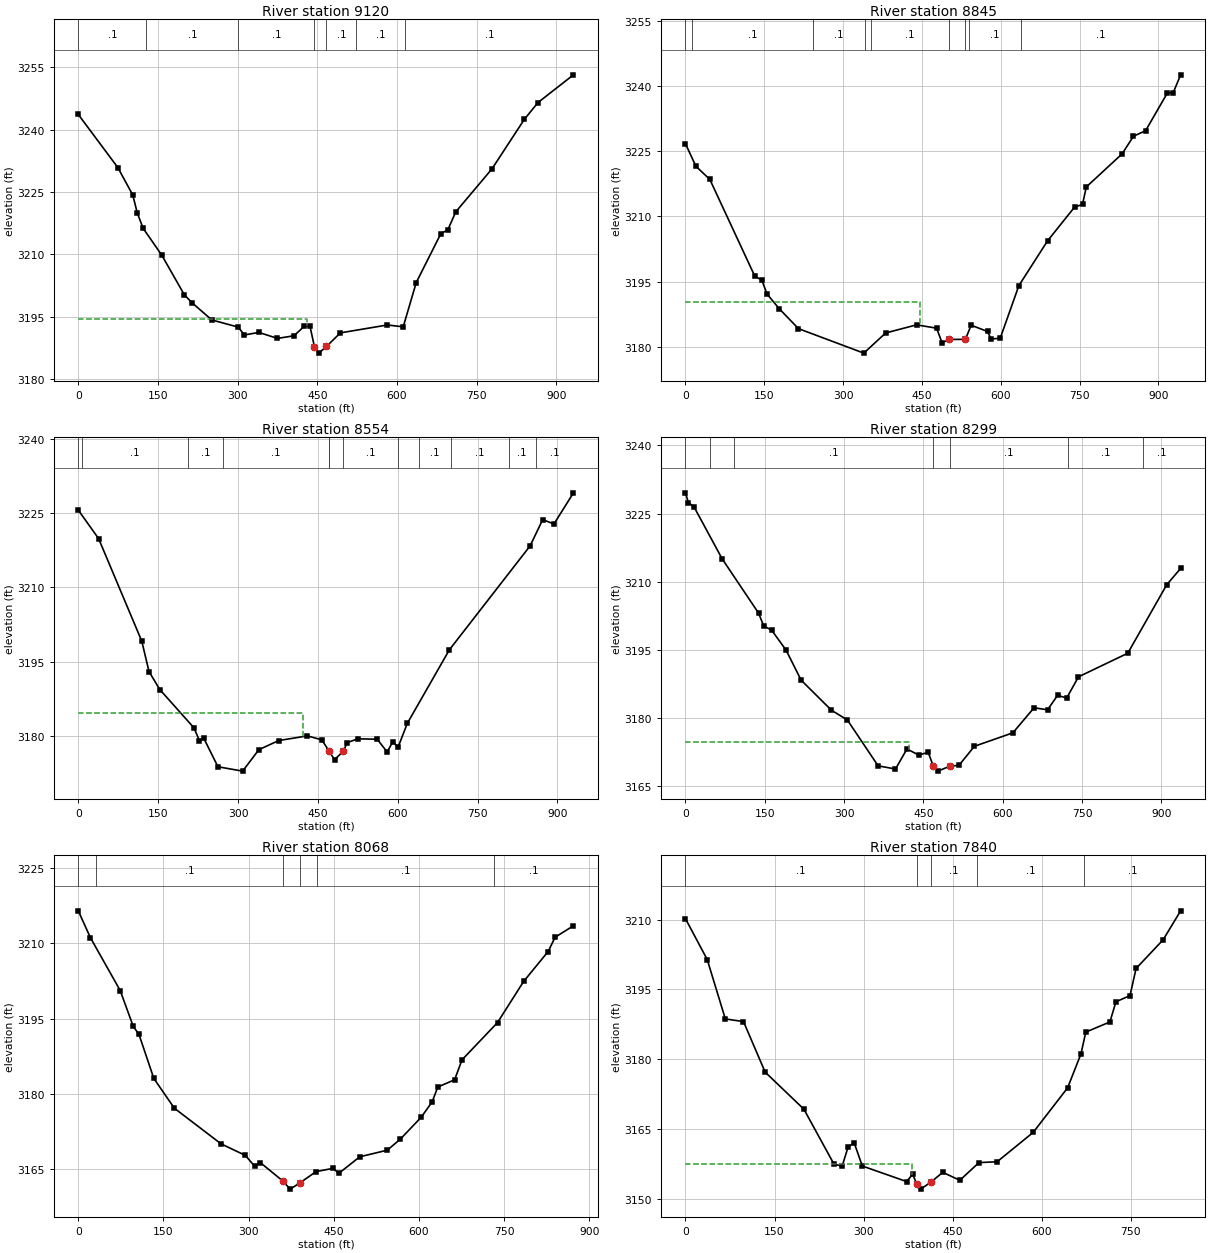
Type RM Length L Ch R = 1 ,9120    ,270,275.5,278.4
XS GIS Cut Line= 3
2107078.00698945408803.8290493792107325.25813535409191.282014623
2107606.77922586409570.982698798
#Sta/Elev= 30
       0 3243.63    74.5 3230.85   102.6 3224.24   111.1 3219.92     122 3216.26
   157.1  3209.8   199.9  3200.2   214.8 3198.26   251.4  3194.2   301.1 3192.48
   312.7 3190.59     340  3191.2     375 3189.76   406.2  3190.4   425.6 3192.71
   436.1 3192.78   444.53187.793   452.8 3186.22  467.223187.815   493.4 3191.09
   581.9 3192.99   611.8 3192.55   636.3 3203.21   682.7 3214.98   695.7 3215.86
   710.8 3220.22   778.9 3230.55   839.8 3242.46   865.6 3246.51   932.3 3253.17
#Mann= 7 ,-1 , 0
       0      .1       0  128.28      .1       0  301.35      .1       0
   444.5    .045       0  467.22      .1       0  523.02      .1       0
  615.95      .1       0
#XS Ineff= 2 , 0
          430.67 3194.37
Permanent Ineff=
       F       F
Bank Sta=444.5,467.22
XS Rating Curve= 0 ,0
Exp/Cntr=0.3,0.1

Type RM Length L Ch R = 1 ,8845    ,279.7,290.7,294.6
XS GIS Cut Line= 4
2106980.65121302408844.2282467932107000.52748561409050.104803547
2107168.81192595409549.8682397162107253.50040486409740.057819963
#Sta/Elev= 30
       0 3226.71    19.9 3221.53    46.3 3218.52     132 3196.21   145.2 3195.37
   155.1 3192.15   178.1 3188.79   214.9 3184.17   339.4 3178.53   380.9 3183.17
   439.8 3185.04   477.9 3184.27   488.3 3180.91   502.4 3181.68   532.8  3181.7
   543.6 3184.96   574.8 3183.51   581.7 3181.77     599 3181.97   634.5 3194.07
     689 3204.36   740.4 3212.13   755.6 3212.76   762.8 3216.78     831  3224.4
   852.6 3228.46   875.6 3229.72   917.2 3238.43     928 3238.42   942.4 3242.59
#Mann= 9 ,-1 , 0
       0      .1       0   12.49      .1       0  242.74      .1       0
  341.68      .1       0  352.32      .1       0   502.4    .045       0
   532.8      .1       0  539.56      .1       0  638.51      .1       0
#XS Ineff= 2 , 0
          445.39  3190.3
Permanent Ineff=
       F       F
Bank Sta=502.4,532.8
XS Rating Curve= 0 ,0
Exp/Cntr=0.3,0.1

Type RM Length L Ch R = 1 ,8554    ,250.1,254.9,254.7
XS GIS Cut Line= 3
2106956.25559253408840.1698559672106827.72402543409354.295796216
2106706.33319211409735.605729133
#Sta/Elev= 30
       0 3225.58    38.2 3219.83   119.3 3199.14   132.8 3193.03   153.1  3189.4
   217.4 3181.66   227.5 3179.09   235.3 3179.67   262.3 3173.83   308.7 3172.95
   339.1 3177.27   376.3 3179.11   430.4 3180.06   457.5 3179.25   470.6 3177.06
     4713176.958   481.4 3175.28   498.1 3176.98   504.8 3178.69   525.1 3179.47
   561.5 3179.38   580.1 3176.81   590.5 3178.84   600.8 3177.81     618 3182.58
     697 3197.41   848.6 3218.36   872.3 3223.66   893.5 3222.79   930.1 3229.07
#Mann= 12 ,-1 , 0
       0      .1       0    7.53      .1       0  206.33      .1       0
  270.98      .1       0   470.6      .1       0     471    .045       0
   498.1      .1       0   600.1      .1       0  639.75      .1       0
  699.25      .1       0  808.23      .1       0  859.48      .1       0
#XS Ineff= 2 , 0
          422.18 3184.77
Permanent Ineff=
       F       F
Bank Sta=471,498.1
XS Rating Curve= 0 ,0
Exp/Cntr=0.3,0.1

Type RM Length L Ch R = 1 ,8299    ,234.2,231.1,221.4
XS GIS Cut Line= 2
2106836.29290593408758.7668035482106430.70480636409602.790049881
#Sta/Elev= 30
       0 3229.57     5.4 3227.41      16  3226.5    69.3 3215.03   138.2 3203.06
     148 3200.22   162.8 3199.33   190.2 3194.91   218.7 3188.29   275.9 3181.68
   306.1 3179.52   364.3 3169.41   397.1 3168.72   418.9 3173.14   440.8 3171.79
     459 3172.38   468.83169.306   477.2 3168.25   499.6 3169.32   517.2 3169.53
   546.3 3173.72   619.1 3176.69   659.2 3182.21   684.7 3181.76   703.6 3184.94
   720.9 3184.37   743.2 3189.03   836.4 3194.23   910.3 3209.36   936.4 3212.91
#Mann= 7 ,-1 , 0
       0      .1       0   46.96      .1       0   91.52      .1       0
   468.8    .045       0   499.6      .1       0  723.44      .1       0
  864.86      .1       0
#XS Ineff= 2 , 0
          422.75 3174.77
Permanent Ineff=
       F       F
Bank Sta=468.8,499.6
XS Rating Curve= 0 ,0
Exp/Cntr=0.3,0.1

Type RM Length L Ch R = 1 ,8068    ,226.3,228.1,229.5
XS GIS Cut Line= 2
2106444.98594576 408744.485336052106383.57661977  409614.2148958
#Sta/Elev= 30
       0 3216.49    21.2 3211.17    73.8 3200.62    96.8 3193.47   106.7 3191.93
     133 3183.12   169.2 3177.19   251.4  3170.1   294.2  3167.8   310.6 3165.64
   320.5 3166.37  359.913162.735   373.1 3161.09  390.053162.318   418.7 3164.58
   448.8 3165.23   458.6 3164.22   495.5 3167.52   544.2 3168.85   567.2 3171.06
   603.8  3175.4   623.1 3178.47     633 3181.41   662.6 3182.86   675.7 3186.83
   738.2 3194.25   784.2 3202.44   827.3 3208.39   839.6 3211.23   871.9 3213.52
#Mann= 6 ,-1 , 0
       0      .1       0   32.01      .1       0  359.91    .045       0
  390.05      .1       0  420.89      .1       0   732.5      .1       0
Bank Sta=359.91,390.05
XS Rating Curve= 0 ,0
Exp/Cntr=0.3,0.1

Type RM Length L Ch R = 1 ,7840    ,214.2,215.8,216.2
XS GIS Cut Line= 2
2106295.03250551408730.2041966322106083.66973928 409537.09628363
#Sta/Elev= 30
       0 3210.19    36.6 3201.41    67.1 3188.65    97.7 3188.08   134.2 3177.21
   199.4 3169.25   250.3 3157.39   263.9 3157.02     274 3161.16   284.2    3162
   297.8 3157.03   372.4 3153.69   382.6 3155.27   389.3 3153.24   396.1 3152.06
  412.85 3153.51   433.4 3155.67   462.1 3153.96   494.3 3157.76     525 3157.95
   585.7 3164.26   643.7 3173.84   666.3 3181.18   674.2 3185.81   714.9    3188
   725.1 3192.34   748.8 3193.67     759  3199.5   804.5 3205.65   834.1 3211.89
#Mann= 5 ,-1 , 0
       0      .1       0   389.3    .045       0  412.85      .1       0
  491.42      .1       0   671.4      .1       0
#XS Ineff= 2 , 0
          381.86 3157.53
Permanent Ineff=
       F       F
Bank Sta=389.3,412.85
XS Rating Curve= 0 ,0
Exp/Cntr=0.3,0.1

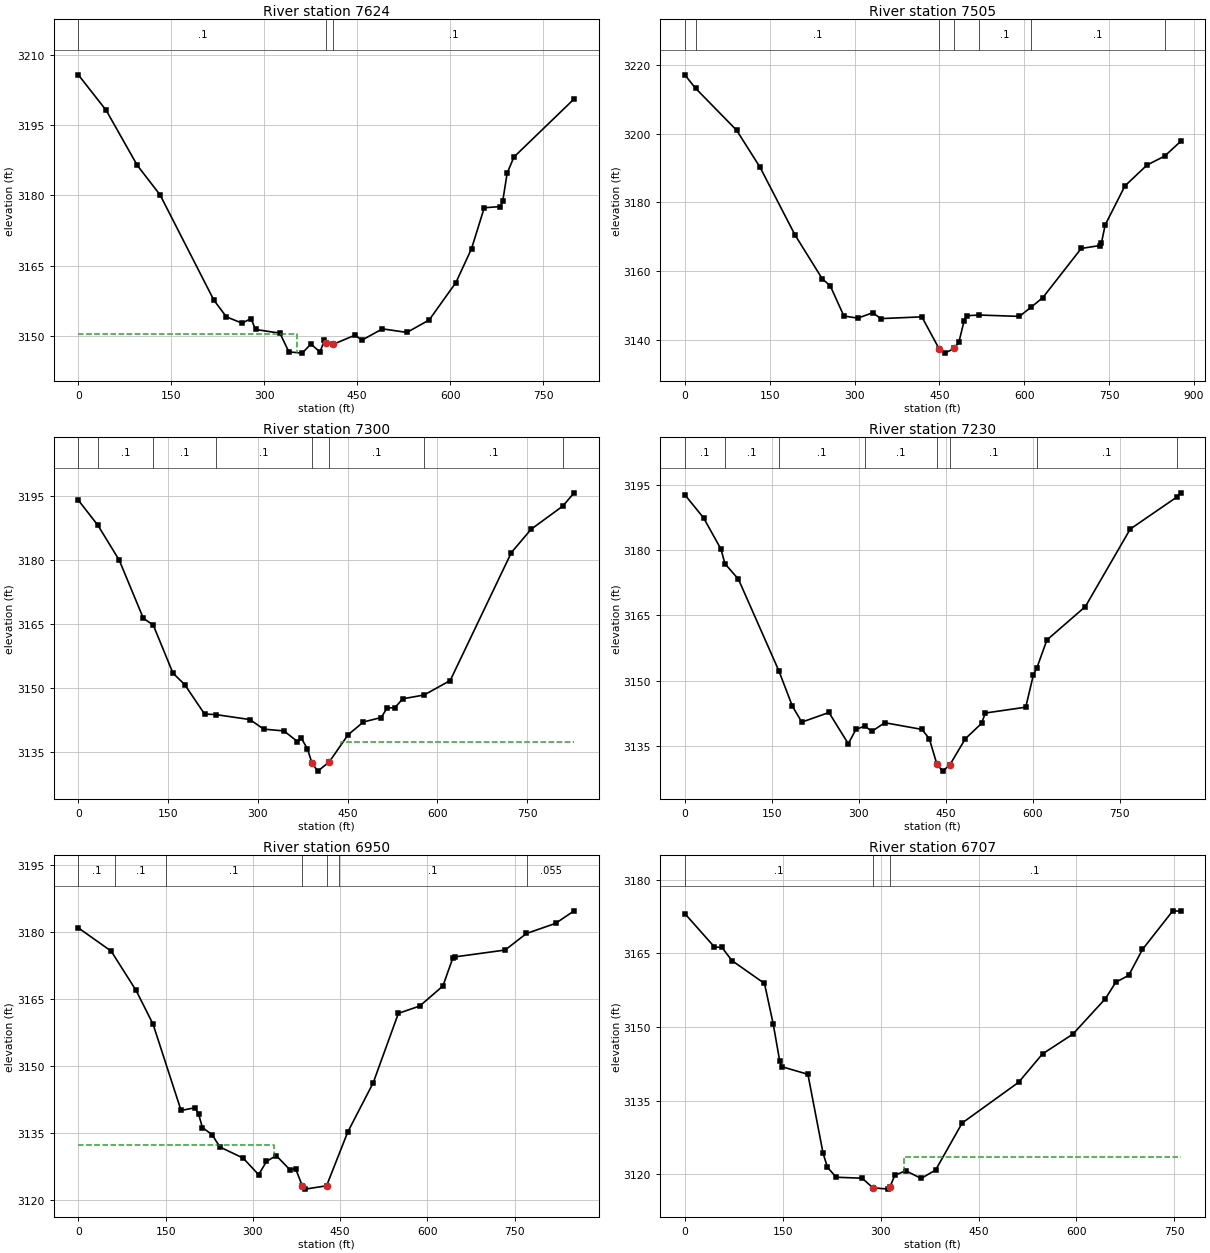
Type RM Length L Ch R = 1 ,7624    ,120.5,119.4,118
XS GIS Cut Line= 2
2106158.88047675408685.3046729052105831.73845689409415.458799907
#Sta/Elev= 30
       0 3205.76      45 3198.17    95.2 3186.42   131.9 3180.13   218.8 3157.64
     239 3154.09   264.2 3152.75   278.6 3153.72   285.9  3151.4   325.3 3150.61
   339.7 3146.62   361.3 3146.35   375.2 3148.28     390  3146.6   397.2 3149.11
     400 3148.41   411.6 3148.26   447.2 3150.22   457.1 3149.08   490.7 3151.53
   530.2 3150.77   566.2 3153.43   609.3 3161.42   634.5 3168.65     655 3177.38
   681.2 3177.64   684.8 3178.78     692 3184.78   702.9 3188.21   800.1 3200.62
#Mann= 3 , 0 , 0
       0      .1       0     400    .045       0   411.6      .1       0
#XS Ineff= 2 , 0
          353.22 3150.43
Permanent Ineff=
       F       F
Bank Sta=400,411.6
XS Rating Curve= 0 ,0
Exp/Cntr(USF)=0,0
Exp/Cntr=0.3,0.1

Type RM Length L Ch R = 1 ,7505    ,209.2,204.8,194.8
XS GIS Cut Line= 2
2106027.97267219408570.253729135 2105759.4846921409404.280276299
#Sta/Elev= 30
       0 3217.12      19 3213.21    91.5    3201   132.9 3190.23   194.9 3170.47
   243.2 3157.68     257 3155.73   281.1 3146.93   305.8  3146.3   331.9 3147.87
   346.6 3146.17   418.9 3146.68   449.2 3137.45   459.6 3136.12  475.963137.475
   484.4 3139.34   493.5 3145.44   498.2    3147   519.6 3147.21   591.3 3146.81
     612  3149.5   632.6 3152.26   700.5 3166.58   733.4 3167.44   736.1 3168.06
   742.9 3173.44   777.7 3184.77   816.8 3190.86   847.9 3193.46   876.2 3197.73
#Mann= 7 ,-1 , 0
       0      .1       0      19      .1       0   449.2    .045       0
  475.96      .1       0   519.6      .1       0     612      .1       0
   847.9     .06       0
Bank Sta=449.2,475.96
XS Rating Curve= 0 ,0
Exp/Cntr=0.5,0.3

Type RM Length L Ch R = 1 ,7300    ,69.7,69.8,69.7
XS GIS Cut Line= 4
2105645.23459253408578.8226096332105680.93760511408925.857676715
2105703.78795311409048.6766567982105740.91911244409401.423982799
#Sta/Elev= 30
       0 3194.04    32.8 3188.13    68.4 3179.97   108.6 3166.37   125.2 3164.77
   158.1 3153.53   177.9  3150.8   210.9 3143.94   229.9  3143.8   286.7 3142.64
   309.8  3140.4   343.5 3139.98   366.1  3137.5   372.8 3138.22   382.8 3135.79
   390.4 3132.45   400.1 3130.56   419.1 3132.69   450.7 3139.07   476.3 3142.07
   506.1 3143.12   515.8 3145.32     529 3145.45   542.2 3147.51   577.7 3148.39
   621.4 3151.79   723.6 3181.77   756.6 3187.23   809.4 3192.64   828.5 3195.76
#Mann= 8 ,-1 , 0
       0      .1       0    32.8      .1       0   125.2      .1       0
   229.9      .1       0   390.4    .045       0   419.1      .1       0
   577.7      .1       0   809.4     .06       0
#XS Ineff= 2 , 0
           370.4  3137.3   439.1          3137.3
Permanent Ineff=
       F       F
Bank Sta=390.4,419.1
XS Rating Curve= 0 ,0
Exp/Cntr=0.5,0.3

Type RM Length L Ch R = 1 ,7230    ,273.5,280.4,284.4
XS GIS Cut Line= 4
2105549.55007261408553.116296217 2105616.6719856408960.132542551
2105633.80941853409051.5329502972105686.65019211 409397.13954255
#Sta/Elev= 30
       0 3192.67    32.5 3187.34    62.5 3180.15    69.1 3176.86    92.4  3173.3
   162.3 3152.22   185.5 3144.14   201.8 3140.47   248.6 3142.68   281.9 3135.51
   295.2  3138.8   310.8 3139.59   322.2 3138.33     345 3140.33   408.9  3138.8
   421.6 3136.69   434.9 3130.76   444.9 3129.22  457.163130.671   483.8 3136.65
   511.7 3140.17   518.3 3142.56     588  3143.9   601.3 3151.38     607 3152.85
   624.5 3159.33   690.9 3167.01   768.2 3184.79   848.1  3192.1   855.1 3193.11
#Mann= 8 ,-1 , 0
       0      .1       0    69.1      .1       0   162.3      .1       0
   310.8      .1       0   434.9    .045       0  457.16      .1       0
     607      .1       0   848.1     .06       0
Bank Sta=434.9,457.16
XS Rating Curve= 0 ,0
Exp/Cntr=0.5,0.3

Type RM Length L Ch R = 1 ,6950    ,238.9,242.8,240.9
XS GIS Cut Line= 2
2105433.87182626408578.8226096332105279.63394576409417.133597046
#Sta/Elev= 30
       0  3180.9    56.5 3175.69    99.3  3166.9   128.5 3159.35   176.6 3140.06
     200 3140.66   206.6 3139.35   213.3 3136.24     230 3134.65   243.3  3131.9
   283.3 3129.41     310 3125.69   323.4 3128.65   340.1 3129.98   363.4 3126.85
   373.6 3127.01   384.8 3123.28   390.1 3122.47   426.8 3123.22   463.1 3135.22
   506.9 3146.24   550.2 3161.78   586.9 3163.42   626.7 3167.89   643.6 3174.07
     647  3174.4   733.7 3175.94   770.4 3179.64   820.4  3181.9   852.4 3184.71
#Mann= 7 ,-1 , 0
       0      .1       0   63.28      .1       0  151.04      .1       0
   384.8    .045       0   426.8      .1       0  447.66      .1       0
  771.71    .055       0
#XS Ineff= 2 , 0
          336.73 3132.31
Permanent Ineff=
       F       F
Bank Sta=384.8,426.8
XS Rating Curve= 0 ,0
Exp/Cntr=0.3,0.1

Type RM Length L Ch R = 1 ,6707    ,159.6,160.7,158
XS GIS Cut Line= 2
2105196.54434031408605.9132070732105069.74306636409354.870264421
#Sta/Elev= 30
       0 3173.09    45.5 3166.28    56.9  3166.2    72.2 3163.52   122.1 3158.86
   135.4 3150.65   145.4 3143.08   148.7 3141.91   188.6 3140.37   211.9 3124.26
   218.6 3121.42   231.9 3119.41   271.8 3119.21     2883117.266   311.7 3116.99
   313.9 3117.33   321.7 3119.79   338.4 3120.74     362 3119.17   384.2 3120.87
   424.9 3130.45   511.4 3138.74     548 3144.52   594.6 3148.55   644.5 3155.79
   660.2  3159.1   680.1 3160.52   701.1 3165.78   747.6 3173.65   759.6 3173.58
#Mann= 3 ,-1 , 0
       0      .1       0     288    .045       0   313.9      .1       0
#XS Ineff= 2 , 0
                          335.08         3123.56
Permanent Ineff=
       F       F
Bank Sta=288,313.9
XS Rating Curve= 0 ,0
Exp/Cntr(USF)=0,0
Exp/Cntr=0.3,0.1

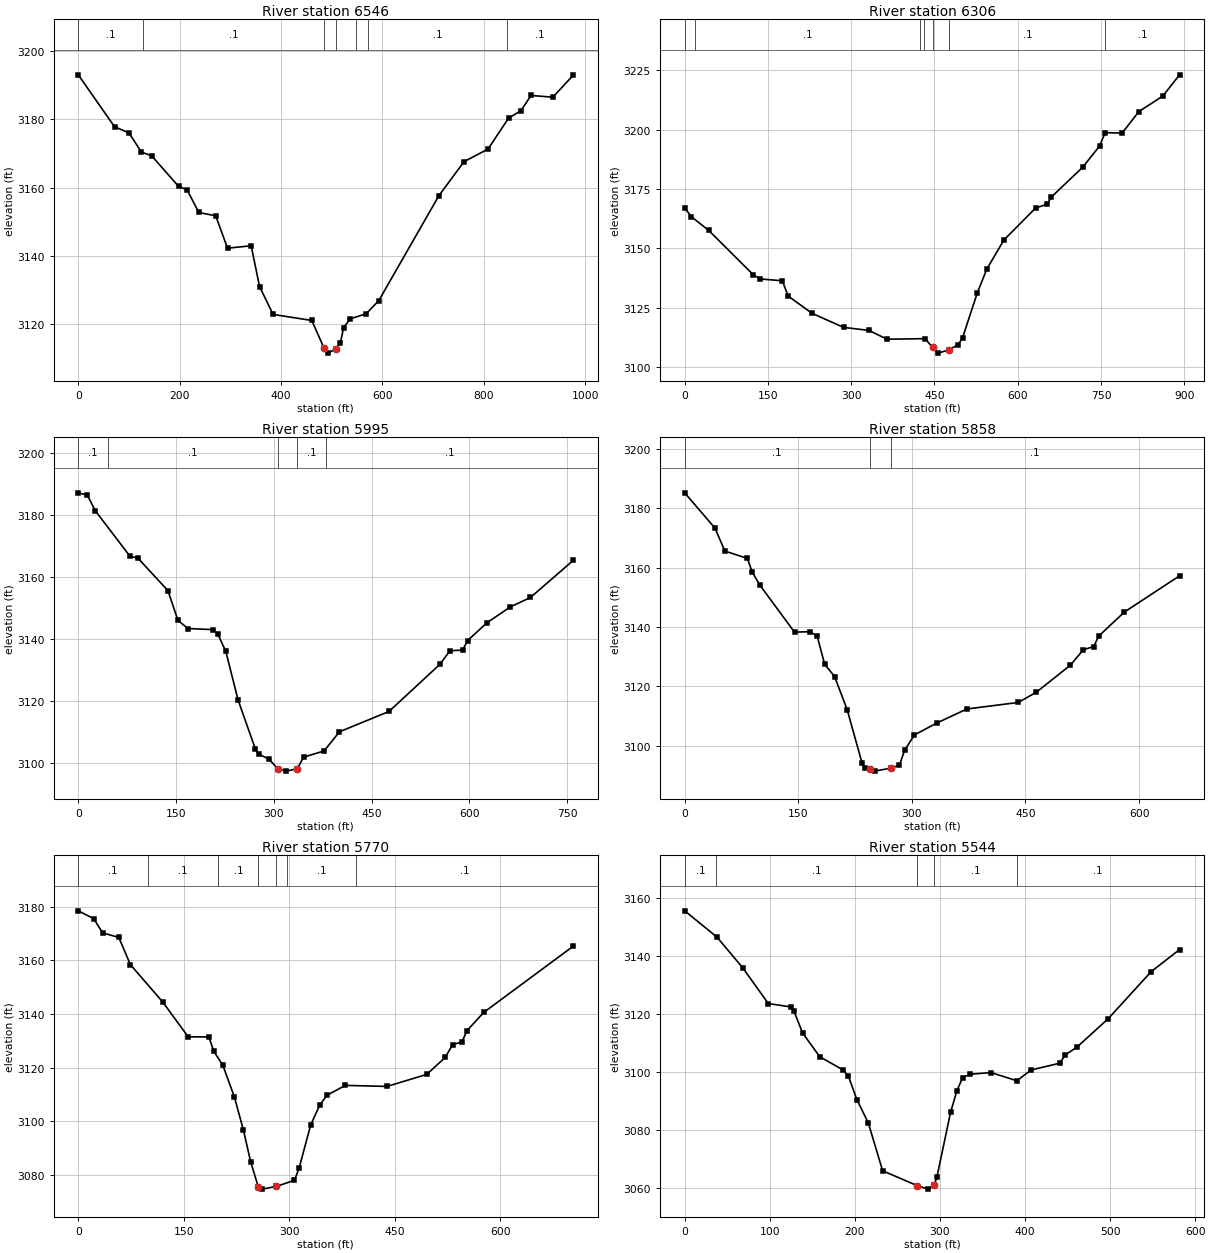
Type RM Length L Ch R = 1 ,6546    ,238.4,240.5,241.5
XS GIS Cut Line= 3
2105092.54934618408436.0099031332105016.85855269408877.301343381
2104958.30519211409402.852129549
#Sta/Elev= 30
       0 3193.01    71.5 3177.81    99.9 3176.01   124.7 3170.36   144.7 3169.32
     198 3160.31   214.6 3159.34   237.9 3152.69   271.2 3151.72   294.5 3142.23
   341.1 3142.94   357.7 3130.99   384.4 3122.83   460.8 3121.07   484.9 3112.95
   493.5  3111.5   508.7 3112.85   516.9 3114.32   523.5 3118.97   536.7 3121.56
   568.1 3123.03   592.9 3126.88   711.7 3157.65   761.2 3167.58   808.6 3171.28
     849 3180.33   873.5 3182.52   893.3 3186.96   936.4 3186.47   976.5 3192.87
#Mann= 7 ,-1 , 0
       0      .1       0  127.47      .1       0   484.9    .045       0
   508.7      .1       0  548.79      .1       0   570.7      .1       0
  846.08      .1       0
Bank Sta=484.9,508.7
XS Rating Curve= 0 ,0
Exp/Cntr=0.3,0.1

Type RM Length L Ch R = 1 ,6306    ,304.3,310.8,314
XS GIS Cut Line= 3
2104936.88331893408443.1506368822104814.06433886408731.632343382
2104675.53607261409292.886470214
#Sta/Elev= 30
       0 3167.03    11.7 3163.31    43.3 3157.48   123.7 3138.76   136.5 3137.01
   175.8 3136.27   186.5 3129.82   229.3 3122.57   286.2 3116.63   331.7 3115.36
   364.6 3111.64   433.1 3111.88   446.5 3108.19   456.7 3105.78  476.533107.212
   492.7 3109.35   500.6 3112.25   527.2 3131.17   544.2 3141.14     575 3153.42
   632.4 3166.95   652.6 3168.46   660.7 3171.57   716.9 3184.08   747.5 3193.04
   757.5 3198.69   787.9 3198.47   818.3 3207.57   861.3 3214.07   891.6 3223.04
#Mann= 7 ,-1 , 0
       0      .1       0    18.7      .1       0  423.81      .1       0
   430.4      .1       0   446.5    .045       0  476.53      .1       0
     758      .1       0
Bank Sta=446.5,476.53
XS Rating Curve= 0 ,0
Exp/Cntr=0.3,0.1

Type RM Length L Ch R = 1 ,5995    ,140.2,137,127.2
XS GIS Cut Line= 3
2104786.92987868408350.322082371 2104425.6136722408931.570263714
2104392.76662502408998.692176715
#Sta/Elev= 30
       0 3187.04    13.9 3186.28    26.3 3181.21    79.5 3166.55    91.1  3166.1
   137.5 3155.55   152.9 3145.95   168.4 3143.34     207 3142.99   214.2  3141.5
   226.3 3135.95   245.2 3120.26   271.7 3104.51   276.5 3102.89     292 3101.38
  306.023098.195     319 3097.43  336.03 3098.21   345.5 3101.93     377 3103.92
   400.6  3110.1   476.6 3116.64   554.7 3131.83   570.1 3136.19   589.5 3136.41
   597.2 3139.47   626.6 3145.16   662.4 3150.27   693.6 3153.34   759.1 3165.27
#Mann= 5 ,-1 , 0
       0      .1       0   45.03      .1       0  306.02    .045       0
  336.03      .1       0  379.53      .1       0
Bank Sta=306.02,336.03
XS Rating Curve= 0 ,0
Exp/Cntr=0.3,0.1

Type RM Length L Ch R = 1 ,5858    ,89.2,88,84
XS GIS Cut Line= 3
2104515.74901358408319.0636184782104483.46095606408685.242669185
2104403.97480981408959.859189144
#Sta/Elev= 30
       0 3185.18    39.9 3173.32    53.1 3165.56    82.7 3163.09    89.3 3158.44
    99.2 3154.12     145 3138.25   165.1  3138.4   174.9 3136.97   184.8 3127.44
     198 3123.27   214.5 3112.16   234.2 3094.17   237.5 3092.53   244.1 3092.18
   250.7 3091.43     272 3092.42   283.6 3093.46   290.3 3098.39   303.4 3103.63
     333 3107.64   372.7 3112.37   440.4 3114.56   464.2 3117.98   509.4 3127.14
   526.4 3132.33   540.1 3133.39   546.9 3136.96   580.7 3145.04   653.5 3157.23
#Mann= 3 , 0 , 0
       0      .1       0   244.1    .045       0     272      .1       0
Bank Sta=244.1,272
XS Rating Curve= 0 ,0
Exp/Cntr(USF)=0,0
Exp/Cntr=0.3,0.1

Type RM Length L Ch R = 1 ,5770    ,222.6,226.1,226.2
XS GIS Cut Line= 3
2104394.19477177408304.622042552 2104419.9010852  408745.9134828
2104372.77289861409002.976616964
#Sta/Elev= 30
       0 3178.51    21.9  3175.6    34.6  3170.3    57.6 3168.58      74 3158.45
     120 3144.49   156.2 3131.49   185.7 3131.44   192.3 3126.23   205.5 3120.84
   221.9 3109.01   234.8  3096.6   244.9 3084.95   255.7 3075.59   261.3 3074.64
  281.49 3075.64   307.3 3077.94   313.9 3082.54   330.3 3098.56   342.9 3105.88
   353.3 3109.65   379.6 3113.36   438.8 3112.97   495.4 3117.47   521.4 3123.78
   532.1 3128.56   545.5  3129.6   552.1 3133.68   576.2 3140.57   703.4 3165.29
#Mann= 7 ,-1 , 0
       0      .1       0   98.91      .1       0  199.17      .1       0
   255.7    .045       0  281.49      .1       0  297.14      .1       0
   395.1      .1       0
Bank Sta=255.7,281.49
XS Rating Curve= 0 ,0
Exp/Cntr=0.3,0.1

Type RM Length L Ch R = 1 ,5544    ,238,238.2,236
XS GIS Cut Line= 2
2104264.23538601408354.606522635 2104139.9882592408923.001383215
#Sta/Elev= 30
       0 3155.65    37.9 3146.61    68.1 3136.06    98.3 3123.68   125.2  3122.5
   128.6 3120.98   138.6 3113.53   158.8 3105.35   185.7 3100.86   192.4  3098.7
   202.4 3090.59   215.9 3082.49   232.7 3066.03     273 3060.94   286.4  3059.7
   293.3 3061.03   296.5 3063.86   312.6 3086.22     320 3093.58   326.7 3098.15
   335.8 3099.33   360.3 3099.88   390.5 3097.06   407.3 3100.78   440.9 3103.11
   447.6 3106.04     461 3108.62     498 3118.49   548.3 3134.66   581.8  3142.3
#Mann= 5 ,-1 , 0
       0      .1       0   37.28      .1       0     273    .045       0
   293.3      .1       0  390.28      .1       0
Bank Sta=273,293.3
XS Rating Curve= 0 ,0
Exp/Cntr=0.3,0.1

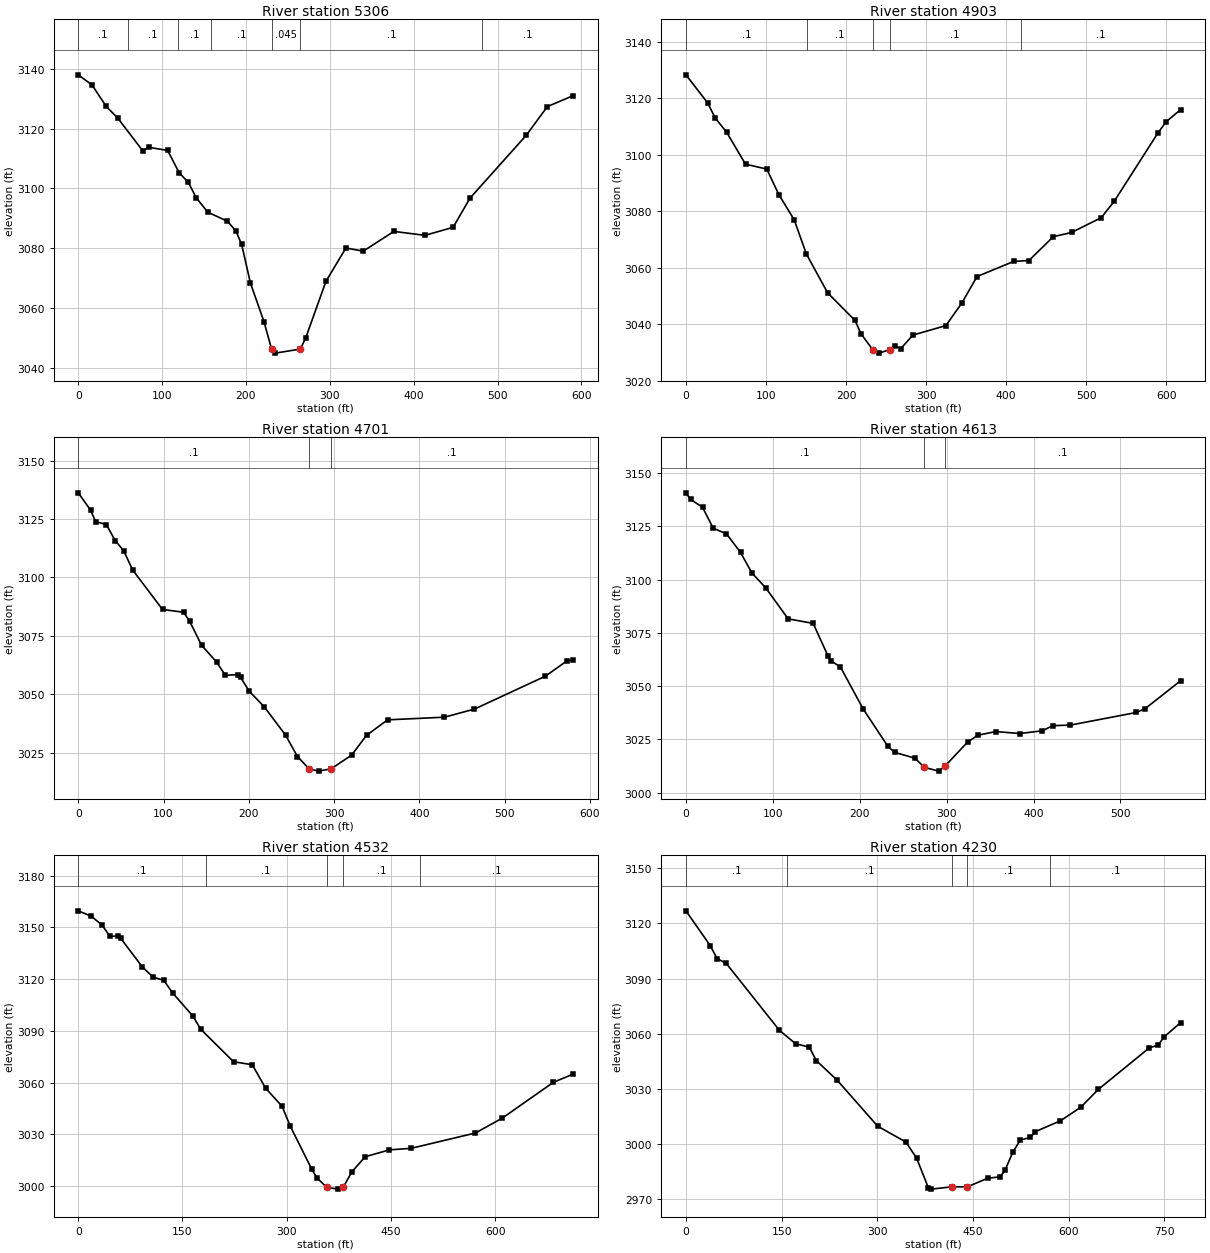
Type RM Length L Ch R = 1 ,5306    ,409.7,402.7,387.6
XS GIS Cut Line= 2
2104037.16300553 408313.190923052103907.20329168  408888.7261893
#Sta/Elev= 30
       0 3137.95    16.5 3134.53    33.3 3127.38    46.8 3123.59      77  3112.5
    83.8 3113.72   106.6 3112.67   120.3 3105.21   131.3 3101.95   140.9 3096.77
   154.4 3092.03   177.9    3089     188 3085.74   194.8 3081.27   205.3 3068.33
   221.7 3055.22  230.643046.124   235.1  3044.9   264.9 3046.27   271.2 3049.96
   295.3 3068.88   319.2 3080.06   339.8 3078.99   376.4  3085.6   413.4 3084.28
     447 3086.96   467.2 3096.74   534.5 3117.82   559.3 3127.31     590 3130.97
#Mann= 7 ,-1 , 0
       0      .1       0   59.35      .1       0   118.8      .1       0
  158.35      .1       0  230.64    .045       0   264.9      .1       0
  481.88      .1       0
Bank Sta=230.64,264.9
XS Rating Curve= 0 ,0
Exp/Cntr=0.3,0.1

Type RM Length L Ch R = 1 ,4903    ,199.1,201.6,203.7
XS GIS Cut Line= 3
2103499.94327945408409.4256387052103622.27308726408618.584013045
2103813.36030352408941.947539538
#Sta/Elev= 30
       0 3128.29    27.3 3118.27    36.4 3113.07    50.8 3107.97    74.4 3096.65
     101 3094.91     116 3085.88   135.2 3076.97   150.4 3064.86     177 3051.07
   211.2 3041.31   218.8 3036.51   233.5 3030.88   241.6 3029.74   254.4    3031
   260.7 3032.43   268.3 3031.34   283.5 3036.13   324.6 3039.48   344.5 3047.44
   363.6 3056.87   409.3 3062.21   428.4 3062.54   458.8 3070.96   481.7 3072.48
   518.6 3077.69   535.1 3083.59   589.7  3107.8   599.8 3111.68   617.9 3115.99
#Mann= 5 ,-1 , 0
       0      .1       0  151.47      .1       0   233.5    .045       0
   254.4      .1       0  418.06      .1       0
Bank Sta=233.5,254.4
XS Rating Curve= 0 ,0
Exp/Cntr=0.3,0.1

Type RM Length L Ch R = 1 ,4701    ,86.3,88,87.7
XS GIS Cut Line= 2
2103365.07340643408470.0349533282103574.43376529409011.211729996
#Sta/Elev= 30
       0 3136.22    14.4 3128.82    20.3 3123.91      33 3122.64    43.2 3115.81
    53.3 3111.44    63.7 3103.24    98.8 3086.32   123.5 3085.12   130.5 3081.38
   144.6 3071.01   162.2 3063.82   172.5 3058.12   186.8 3058.43   190.3 3057.31
   200.4 3051.39   218.2 3044.62   243.1 3032.57   257.1 3023.37   270.7 3018.13
   281.8 3017.14   296.63018.138   320.5 3023.95   338.1 3032.45   362.8 3039.08
   429.5 3040.22   464.7 3043.69   547.9 3057.77   573.3 3064.34   580.3 3064.82
#Mann= 3 ,-1 , 0
       0      .1       0   270.7    .045       0   296.6      .1       0
Bank Sta=270.7,296.6
XS Rating Curve= 0 ,0
Exp/Cntr(USF)=0,0
Exp/Cntr=0.3,0.1

Type RM Length L Ch R = 1 ,4613    ,84.9,81.5,79
XS GIS Cut Line= 2
2103300.86001148408494.8383859342103473.35187946409037.331894419
#Sta/Elev= 30
       0  3140.7     5.3 3137.61    19.1 3133.93    31.4 3124.08    46.6 3121.49
    62.8 3112.75    75.8 3103.18      92 3096.03   117.6 3081.59   146.4 3079.46
   163.7    3064   167.1 3061.81   177.7 3059.06   203.8  3039.4   232.4 3021.75
   240.4 3018.95   263.5 3016.23   274.4 3011.91     291 3010.16     298 3012.48
     324 3023.73   335.8 3026.99   356.5 3028.71   384.1  3027.8   410.2 3029.08
   421.9 3031.48   442.5 3031.76   518.3 3037.67   528.6 3039.53   569.3 3052.58
#Mann= 3 ,-1 , 0
       0      .1       0   274.4    .045       0     298      .1       0
Bank Sta=274.4,298
XS Rating Curve= 0 ,0
Exp/Cntr(USF)=0,0
Exp/Cntr=0.3,0.1

Type RM Length L Ch R = 1 ,4532    ,304,301.6,299.5
XS GIS Cut Line= 2
 2103117.4489657408487.4225299662103494.47445837409091.520403132
#Sta/Elev= 30
       0 3159.55    18.6 3156.42      34 3151.41    45.6 3144.72    57.2 3144.98
    61.1 3143.61      92 3127.12   107.5 3121.15     123 3119.27   136.2 3111.74
   164.8 3098.64     176 3091.01   223.5 3072.06   250.5 3070.32   269.5  3056.8
   293.4 3046.21   304.7 3035.06   336.2 3009.65   343.4 3004.78   357.6 2999.25
   374.3 2998.22   381.5 2999.39   393.7 3008.21     413    3017   447.8 3020.98
   479.1 3021.87   571.6 3030.75   610.1 3039.33   683.7 3060.11   712.1 3064.87
#Mann= 5 ,-1 , 0
       0      .1       0  183.36      .1       0   357.6    .045       0
   381.5      .1       0  492.53      .1       0
Bank Sta=357.6,381.5
XS Rating Curve= 0 ,0
Exp/Cntr=0.3,0.1

Type RM Length L Ch R = 1 ,4230    ,307.5,322.5,323.9
XS GIS Cut Line= 3
2102857.78648177 408613.074791142102984.39825387 408886.12794078
  2103335.625325409205.442588866
#Sta/Elev= 30
       0  3126.9      38 3107.99    48.8 3100.91    63.3 3098.22   146.5 3061.81
   171.8 3054.52   193.5 3052.59   204.3 3045.33   236.9 3034.69   300.6 3009.56
   345.1 3000.86   361.9 2991.96   380.3 2975.81     385 2975.26   417.6 2976.56
   440.9 2976.44     473  2981.2   492.5 2981.94   500.3 2985.51   512.8 2995.66
   524.5 3002.04   540.2 3003.46   547.7 3006.56   587.2 3012.49   619.3 3019.94
   646.6  3029.6   726.6 3052.26   740.5 3053.73   749.7 3058.23   775.7 3065.99
#Mann= 5 ,-1 , 0
       0      .1       0  157.81      .1       0   417.6    .045       0
   440.9      .1       0  571.53      .1       0
Bank Sta=417.6,440.9
XS Rating Curve= 0 ,0
Exp/Cntr=0.3,0.1

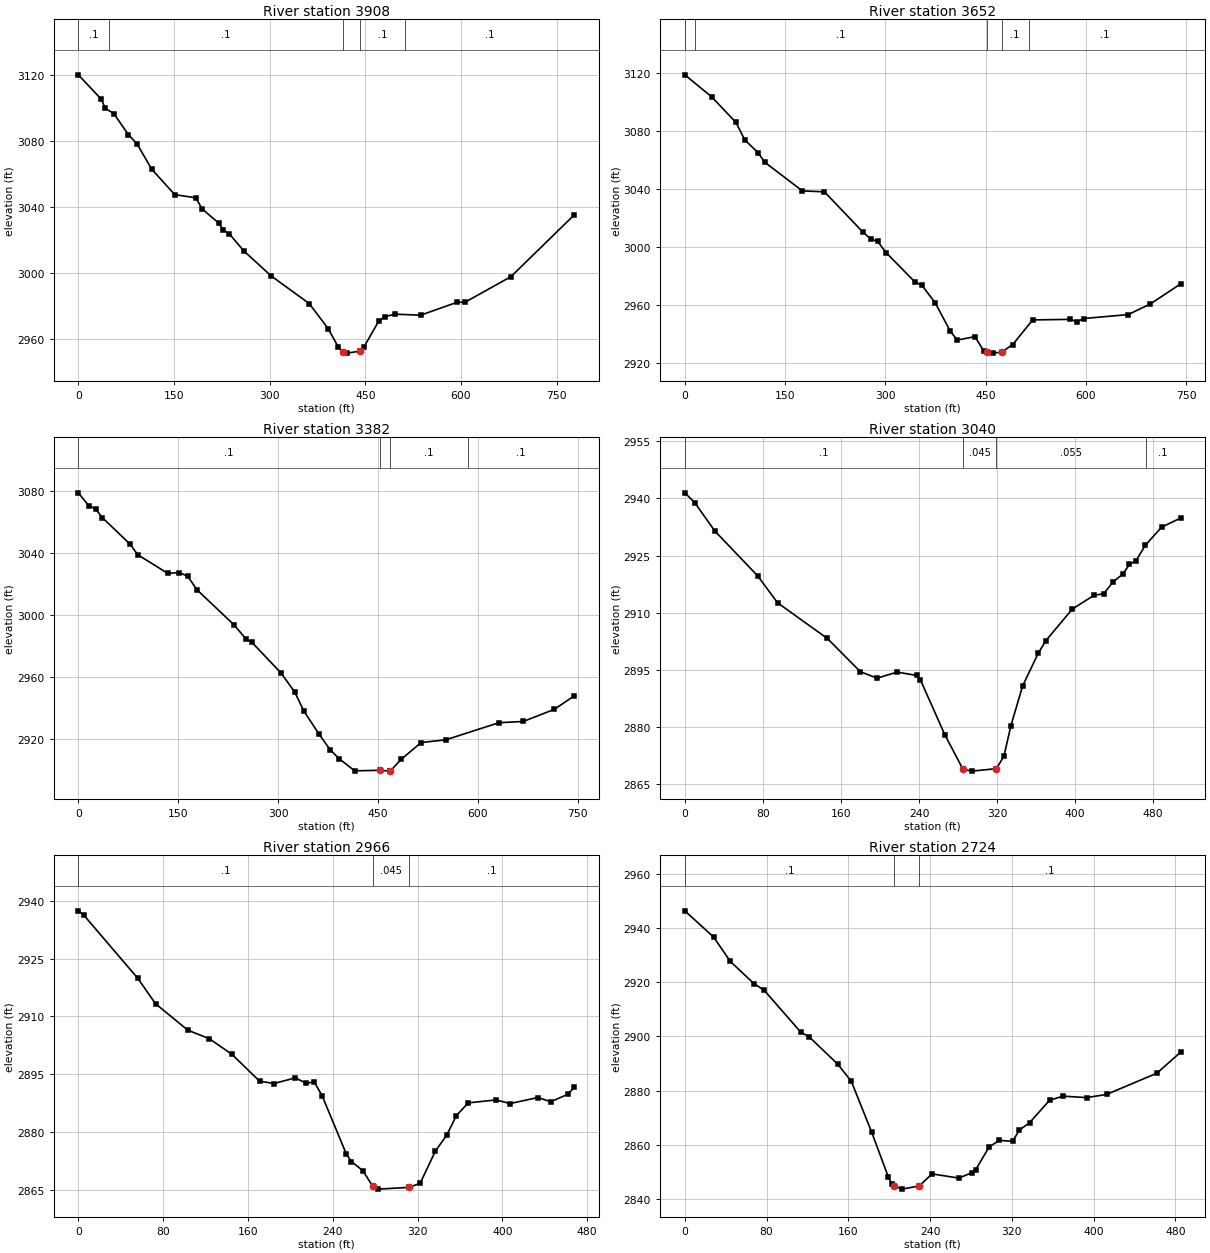
Type RM Length L Ch R = 1 ,3908    ,250.8,255.8,256
XS GIS Cut Line= 3
2102767.55760512408644.5163758842102798.97650552408992.979589716
2102841.82025185409418.561743796
#Sta/Elev= 30
       0 3120.28      36 3105.47    42.5 3099.85    55.7 3096.72    78.4 3083.96
      92 3078.38     115 3062.96   151.3 3047.43   184.2 3045.56   194.1 3038.82
   220.5 3030.04     227 3026.01   236.9 3023.57   259.7 3013.16   302.8 2997.95
   362.1 2981.27   391.8 2966.03   407.3 2955.11   414.9 2951.72   421.4 2951.13
   441.2  2952.3   447.8 2954.77   470.9 2970.44   480.8 2973.35   497.2 2974.79
   536.9  2974.2   594.5 2982.12   606.1 2981.98   678.6 2997.66   777.6 3035.11
#Mann= 5 ,-1 , 0
       0      .1       0   47.41      .1       0   414.9    .045       0
   441.2      .1       0  512.65      .1       0
Bank Sta=414.9,441.2
XS Rating Curve= 0 ,0
Exp/Cntr=0.3,0.1

Type RM Length L Ch R = 1 ,3652    ,267.7,269.9,269.2
XS GIS Cut Line= 3
2102620.46045837408637.3759702152102563.68808838409056.790284508
2102515.28982696409371.433229133
#Sta/Elev= 30
       0 3118.93      40 3103.79    76.5 3086.03    89.7 3073.98   109.6 3065.13
   119.5 3058.57   175.8 3038.74   208.9 3038.09     266 3010.43   278.4 3005.36
   288.3  3003.9     301 2996.11   344.6  2975.6   354.6 2973.51   374.4 2961.49
   397.2 2941.69   407.5 2935.64     434 2938.05   447.3 2927.99  451.312927.092
   460.6 2926.63   473.82927.319   490.5 2932.54   520.3 2949.58   576.8 2949.96
   586.7 2948.38   596.7 2950.54   663.1 2953.26   696.3 2960.61   741.6 2974.46
#Mann= 5 ,-1 , 0
       0      .1       0   15.78      .1       0  451.31    .045       0
   473.8      .1       0   514.7      .1       0
Bank Sta=451.31,473.8
XS Rating Curve= 0 ,0
Exp/Cntr=0.3,0.1

Type RM Length L Ch R = 1 ,3382    ,336.3,341.7,340.3
XS GIS Cut Line= 3
 2102411.9539856408593.1040771312102322.08734811 408930.47688418
2102253.14886981409319.861655542
#Sta/Elev= 30
       0 3078.73    15.6 3070.49    25.8 3068.36    35.9 3062.82    78.2 3045.48
    88.9 3038.96   134.4 3026.85   151.4  3027.4     164 3025.09   178.5 3016.16
   233.7 2993.78   252.4 2984.31   260.5 2982.55   304.2  2962.8   324.8 2950.59
   338.6 2938.29   361.7  2923.2   378.3 2913.25   391.6 2907.57     415 2899.73
   452.52900.045   468.3 2899.53   468.5 2899.59   484.9 2907.14   514.9 2917.96
   551.6 2919.65   631.5  2930.7   668.2 2931.51   714.8 2939.31   744.6 2947.96
#Mann= 4 ,-1 , 0
       0      .1       0   452.5    .045       0   468.5      .1       0
  585.36      .1       0
Bank Sta=452.5,468.5
XS Rating Curve= 0 ,0
Exp/Cntr=0.3,0.1

Type RM Length L Ch R = 1 ,3040    ,60,74.7,93.9
XS GIS Cut Line= 3
2102066.34706527408778.7605299652102003.50959253409011.545169383
2101976.37513235409277.176855966
#Sta/Elev= 30
       0 2941.49    10.2 2938.91    30.6  2931.5    74.8 2919.61    95.1 2912.56
   146.1 2903.18   179.9 2894.45   197.1 2892.73   217.5 2894.34   237.9 2893.45
   241.5 2892.27   266.7 2877.73   285.1 2868.78     294 2868.29   319.3 2868.93
     327 2872.21   334.2 2880.25   346.2  2890.7   362.2 2899.31   370.1 2902.64
   397.1 2910.92   419.4 2914.54   429.2 2914.94   439.1 2918.11     449 2920.14
   455.6 2922.65   462.2 2923.58   472.1 2927.75   488.6 2932.46   508.1 2934.85
#Mann= 4 ,-1 , 0
       0      .1       0   285.1    .045       0   319.3    .055       0
  472.23      .1       0
Bank Sta=285.1,319.3
XS Rating Curve= 0 ,0
Exp/Cntr=0.3,0.1

Type RM Length L Ch R = 1 ,2966    ,250.7,241.7,219.8
XS GIS Cut Line= 4
2102051.75410168408786.8850780032101995.70290328 409009.83029411
2101886.74945021409058.9538163032101792.28113831409130.119944608
#Sta/Elev= 30
       0 2937.42     5.2 2936.29    55.9 2919.97    72.8 2913.31   103.3 2906.44
   123.6 2904.23     145 2900.15   170.9 2893.22   184.4  2892.6   204.7 2894.06
   214.9 2892.68   222.5 2893.03   229.9 2889.46   252.9 2874.24   257.6 2872.36
   268.4 2869.97   277.7 2865.93   282.8 2865.19   311.6 2865.64   322.4 2866.67
   336.7 2875.02   347.5 2879.21   356.6 2884.27   367.8 2887.58   394.1 2888.34
   407.2  2887.4   433.5 2888.97   445.6 2887.87   461.7  2889.8   467.7  2891.6
#Mann= 3 ,-1 , 0
       0      .1       0   277.7    .045       0   311.6      .1       0
Bank Sta=277.7,311.6
XS Rating Curve= 0 ,0
Exp/Cntr(USF)=0,0
Exp/Cntr=0.3,0.1

Type RM Length L Ch R = 1 ,2724    ,188.6,193.2,195.6
XS GIS Cut Line= 2
 2101812.1405527408658.7978433822101780.72165227409142.933029965
#Sta/Elev= 30
       0 2946.45    28.2 2936.76    44.6 2927.73    67.6 2919.56    77.5 2917.16
   113.6 2901.55   121.4 2899.98   149.8 2889.71     163 2883.38   182.7 2864.79
   199.1 2848.14   202.4 2845.47   204.7 2844.77   212.3 2843.57   229.4 2844.72
   241.9 2849.19   268.2 2847.66   281.3  2849.7   284.6 2850.71   297.7 2859.09
   307.6 2861.58   320.8 2861.25   327.3 2865.38   337.5 2868.16   356.9  2876.4
   370.1 2877.95   393.1  2877.4   412.8 2878.58   462.1 2886.45   485.2 2894.22
#Mann= 3 ,-1 , 0
       0      .1       0   204.7    .045       0   229.4      .1       0
Bank Sta=204.7,229.4
XS Rating Curve= 0 ,0
Exp/Cntr=0.3,0.1