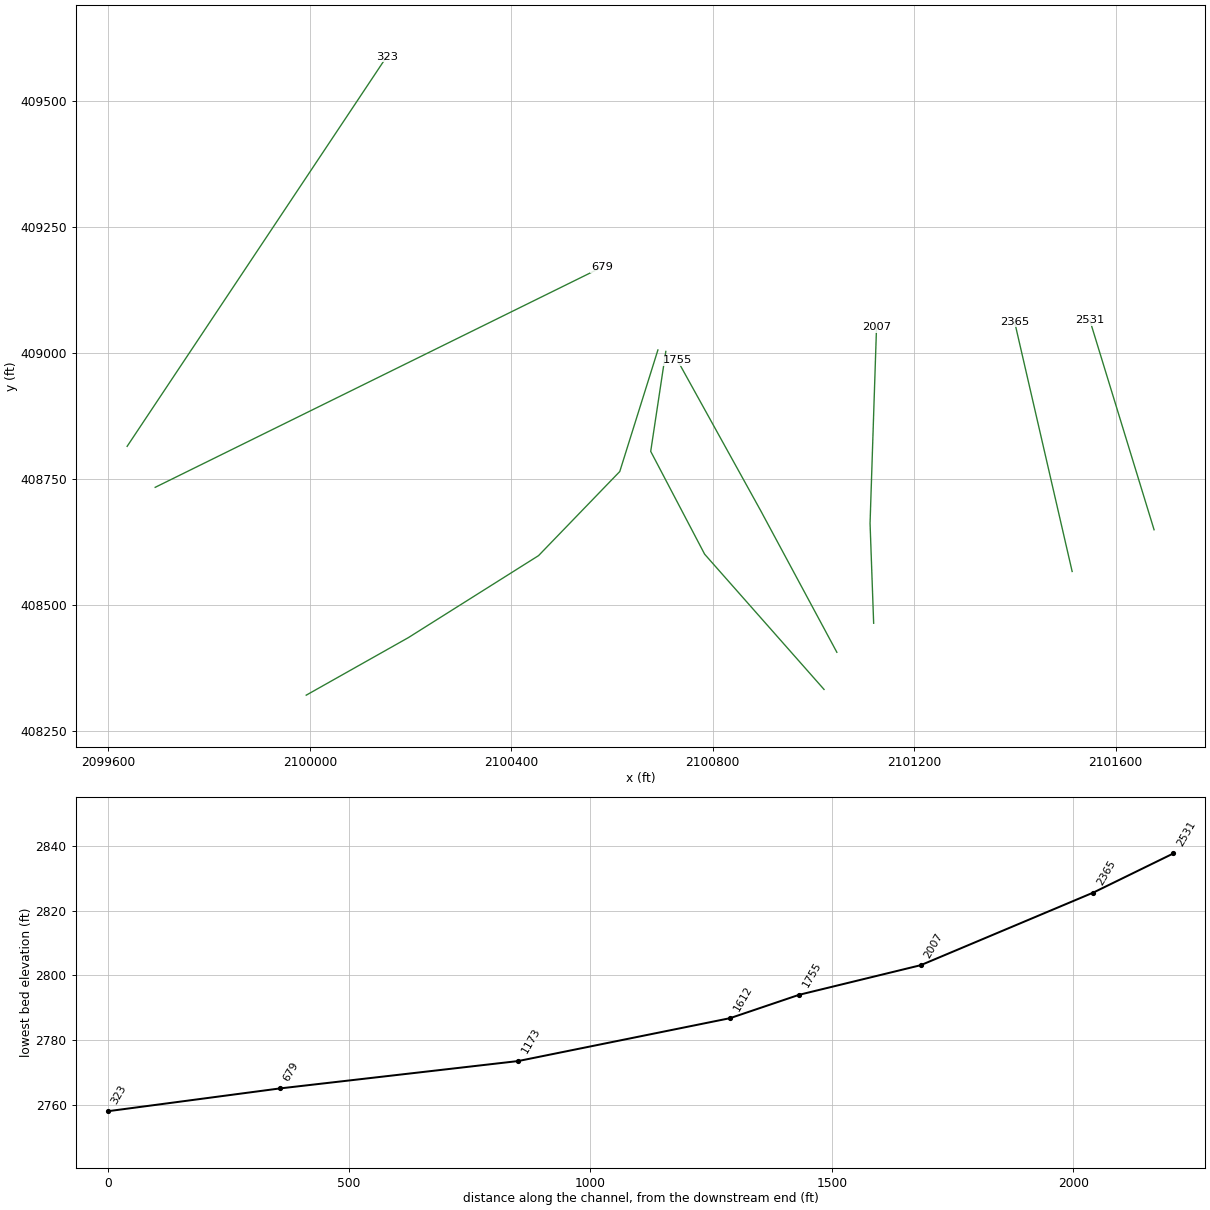
HEC-RAS study MIDDLEBR.prj: MIDDLEBR

--- MIDDLEBR.g01 (geometry) --- (continued)

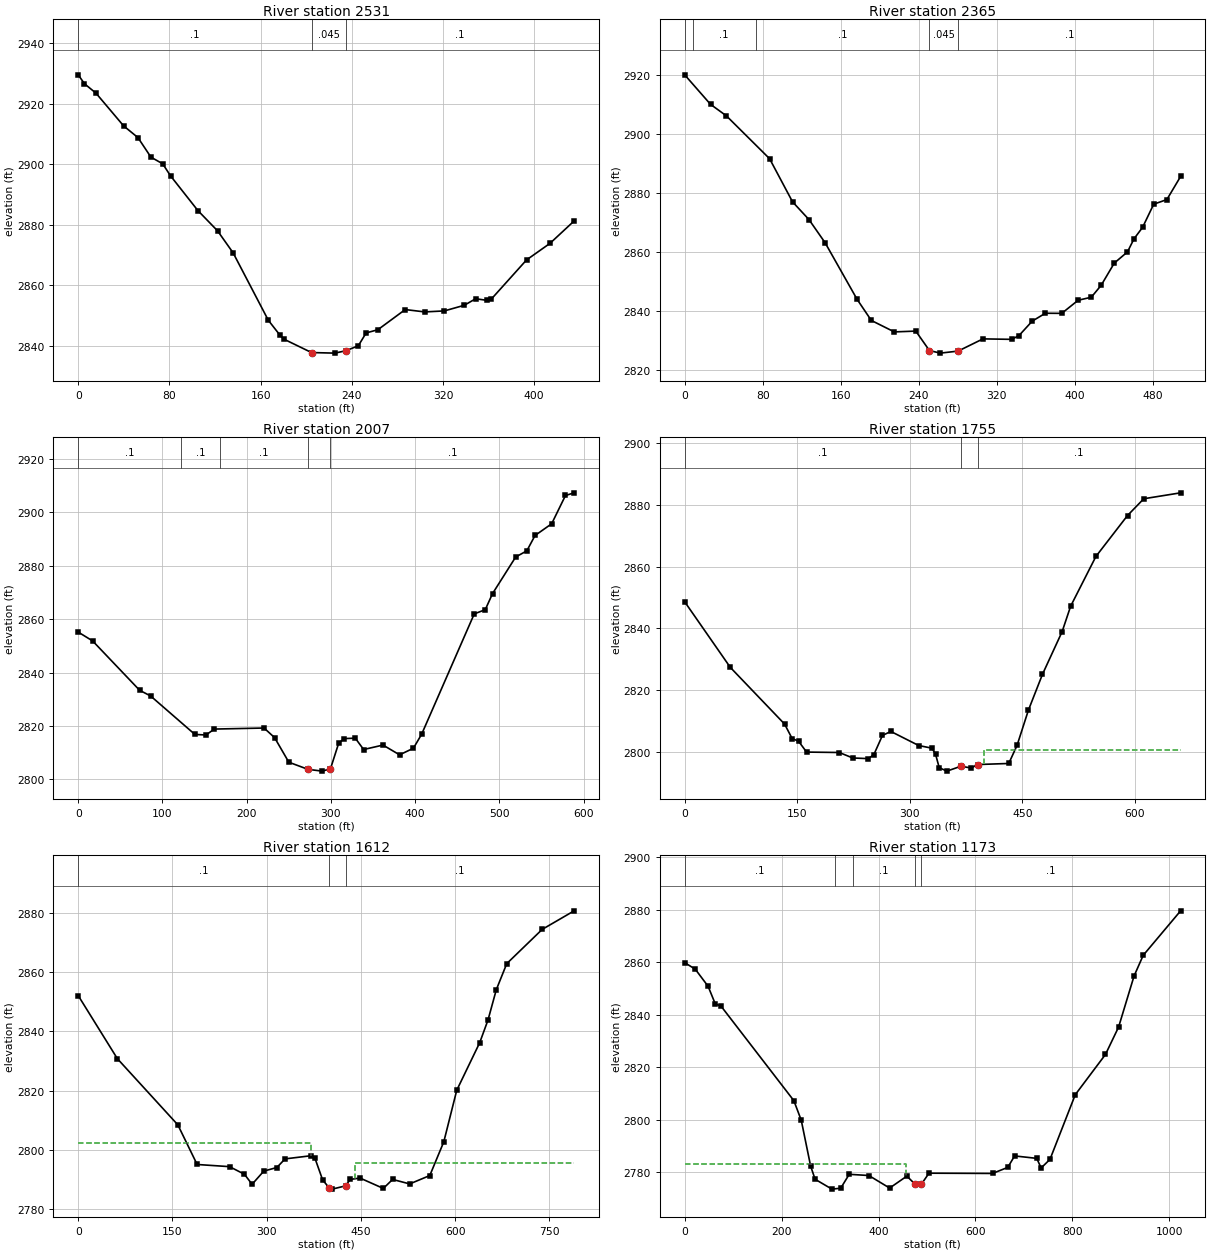
Type RM Length L Ch R = 1 ,2531    ,166.1,165.8,163.7
XS GIS Cut Line= 2
 2101676.3300325 408648.821389562101548.81724935409064.792968751
#Sta/Elev= 30
       0 2929.56     5.5 2926.61    15.6  2923.5    39.8 2912.71    52.4 2908.83
    63.8 2902.37    74.1 2900.18      81  2896.2     105 2884.73   122.2 2878.06
   135.9 2870.77   166.8 2848.49   177.1 2843.54   180.5 2842.26   204.7 2837.84
   225.1 2837.65   234.7 2838.43   245.7 2840.06   252.6 2844.32   262.9 2845.38
   286.9 2852.04     304 2851.26   321.2 2851.59   338.7 2853.45   348.7 2855.61
     359 2855.06   362.4 2855.48   393.3 2868.42   413.9  2873.9   435.1 2881.31
#Mann= 3 ,-1 , 0
       0      .1       0   204.7    .045       0   234.7      .1       0
Bank Sta=204.7,234.7
XS Rating Curve= 0 ,0
Exp/Cntr(USF)=0,0
Exp/Cntr=0.3,0.1

Type RM Length L Ch R = 1 ,2365    ,361,357.7,353
XS GIS Cut Line= 2
2101513.66181895408565.9696169642101399.41171935409061.529649466
#Sta/Elev= 30
       0 2919.89    26.5 2909.89    42.8 2905.98    87.1 2891.45   110.6 2876.85
   127.5 2870.81     144 2862.98   176.8  2843.8   191.4 2836.64     215 2832.75
     237 2833.03  250.972826.442   262.1 2825.56   280.4 2826.25   305.9 2830.39
   335.5 2830.23   342.9 2831.53   356.4  2836.4   369.9 2839.08   386.7 2839.04
   403.5 2843.48     417 2844.51   427.1 2848.54   440.6 2856.09   454.1 2859.87
   460.8 2864.31   469.6 2868.19     481 2876.04   494.5 2877.61   508.6 2885.45
#Mann= 5 ,-1 , 0
       0      .1       0     8.5      .1       0   72.65      .1       0
  250.97    .045       0   280.4      .1       0
Bank Sta=250.97,280.4
XS Rating Curve= 0 ,0
Exp/Cntr=0.3,0.1

Type RM Length L Ch R = 1 ,2007    ,246.4,251.9,258.7
XS GIS Cut Line= 3
2101119.49856529408463.1443632992101112.35783154408661.654136881
2101125.21115229409051.532950297
#Sta/Elev= 30
       0 2855.18    17.1 2851.87    72.9 2833.39      86 2831.24   138.5 2816.85
   151.7 2816.64   161.5 2818.86   220.6 2819.25   233.1 2815.66     250 2806.45
  272.712803.783   289.5 2803.11   299.4 2803.95   309.2 2813.58   315.8 2815.29
   328.9 2815.46   338.8  2811.2   361.8 2812.87   381.5 2809.21   397.9 2811.69
   407.7 2816.95   470.1 2861.99   483.2 2863.58   491.8 2869.58   519.3  2883.3
   532.5  2885.6   542.3 2891.36     562 2895.74   578.4 2906.33   588.7 2907.33
#Mann= 5 ,-1 , 0
       0      .1       0  121.99      .1       0  167.98      .1       0
  272.71    .045       0   299.4      .1       0
Bank Sta=272.71,299.4
XS Rating Curve= 0 ,0
Exp/Cntr=0.3,0.1

Type RM Length L Ch R = 1 ,1755    ,142.9,143.1,141.1
XS GIS Cut Line= 3
2101046.41011559408405.5531622062100894.95962203408687.123093892
2100729.64394244408985.757869923
#Sta/Elev= 30
       0 2848.62    60.8 2827.45   133.2 2809.14   143.2 2804.49   151.8 2803.61
   162.5 2800.11   206.1 2799.97     224 2798.21   244.8 2797.99   252.2  2799.3
   263.6 2805.47   274.8 2806.77     312 2802.22   329.7 2801.36   334.5 2799.35
   339.3 2795.08   349.5 2793.96   368.2 2795.53     382 2794.97   390.6 2796.09
     432 2796.43   443.1 2802.29   458.2 2813.64   476.9 2825.18   503.2 2839.01
   514.5 2847.19   548.2 2863.25   590.3 2876.45     612 2881.87   661.1 2883.78
#Mann= 3 ,-1 , 0
       0      .1       0   368.2    .045       0   390.6      .1       0
#XS Ineff= 2 , 0
                          399.32         2800.65
Permanent Ineff=
       F       F
Bank Sta=368.2,390.6
XS Rating Curve= 0 ,0
Exp/Cntr(USF)=0,0
Exp/Cntr=0.3,0.1

Type RM Length L Ch R = 1 ,1612    ,447.3,438.8,421.8
XS GIS Cut Line= 4
2101020.95775187408331.756502718 2100783.8886722  408600.2444828
2100676.77897829408804.4668433822100706.76973194409002.976616964
#Sta/Elev= 30
       0 2852.08    62.4 2830.76   158.6 2808.44   189.3 2795.06   240.9 2794.33
   264.6 2791.76   276.8 2788.37   295.4 2792.82   316.2 2794.04   329.3 2796.95
   370.8 2798.02     377 2797.09   389.1 2789.85  399.152787.257   404.2 2786.74
   425.6 2787.84   432.9 2790.01   448.6 2790.48   485.7 2786.98   500.5 2790.01
   527.7  2788.5   559.7 2791.33     582 2802.73   602.6 2820.12   639.2 2836.21
   652.4 2843.87   665.6 2854.09   682.2 2862.87   738.6 2874.43   789.5  2880.7
#Mann= 3 ,-1 , 0
       0      .1       0  399.15    .045       0   425.6      .1       0
#XS Ineff= 2 , 0
          369.89 2802.31  440.97         2795.53
Permanent Ineff=
       F       F
Bank Sta=399.15,425.6
XS Rating Curve= 0 ,0
Exp/Cntr=0.3,0.1

Type RM Length L Ch R = 1 ,1173    ,496.3,494.1,490.3
XS GIS Cut Line= 5
2099992.70587134408320.331656799 2100195.5000852408434.581756383
2100453.99136612408597.3881893012100615.36965227408764.479062468
2100691.06044579409005.832910463
#Sta/Elev= 30
       0 2859.85    21.9 2857.33    48.3 2850.83    63.3 2844.03    74.6 2843.36
   225.3 2807.22   240.6 2799.74   259.9  2782.3   269.1 2777.26   303.9 2773.49
     322 2773.84   339.6 2779.14   380.1 2778.68     423  2773.9   458.6 2778.46
   475.2  2775.4   488.7 2775.42   504.2 2779.57   635.3 2779.47   666.8 2781.78
   680.9 2786.15   726.5 2785.22   735.7 2781.57   753.9 2784.84   806.1  2809.5
   868.4 2824.83   895.5 2835.28   927.4 2854.73   946.3 2862.63  1023.5 2879.59
#Mann= 5 ,-1 , 0
       0      .1       0  310.07      .1       0  348.22      .1       0
   475.2    .045       0   488.7      .1       0
#XS Ineff= 2 , 0
          457.05 2783.07
Permanent Ineff=
       F       F
Bank Sta=475.2,488.7
XS Rating Curve= 0 ,0
Exp/Cntr=0.3,0.1

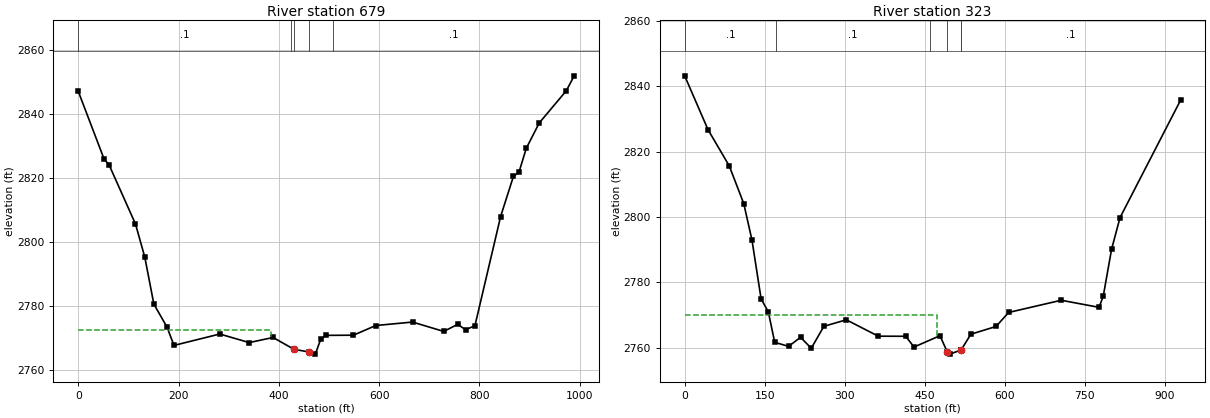
Type RM Length L Ch R = 1 ,679     ,352,356.2,365.1
XS GIS Cut Line= 2
2099692.79931894408733.0604901312100579.66631162409170.067490131
#Sta/Elev= 30
       0 2847.26    51.4 2826.11    61.6 2824.19   114.2 2805.71   132.7 2795.38
   150.8 2780.68   176.8 2773.54     191 2767.75   282.2 2771.31   340.9 2768.63
   388.5 2770.23  430.112766.523  460.222765.692   472.7 2765.02   483.6 2769.73
   494.6 2770.89   548.7 2770.94   593.3 2773.97   666.5 2775.05   728.7 2772.12
   756.6 2774.34   772.2 2772.64   790.9 2773.92   842.1 2808.06   867.7 2820.65
   878.7 2821.92   893.3 2829.42   919.2 2837.35   973.1 2847.41   988.7 2852.07
#Mann= 5 ,-1 , 0
       0      .1       0  423.77      .1       0  430.11    .045       0
  460.22      .1       0   508.5      .1       0
#XS Ineff= 2 , 0
          384.83 2772.56
Permanent Ineff=
       F       F
Bank Sta=430.11,460.22
XS Rating Curve= 0 ,0
Exp/Cntr=0.3,0.1

Type RM Length L Ch R = 1 ,323     ,319.92,322.98,326.04
XS GIS Cut Line= 2
2099637.10225186408814.4635425512100152.65633887409588.508910462
#Sta/Elev= 30
       0 2843.27    43.8 2826.76    83.6 2815.66   110.8 2804.11   126.2 2792.92
   143.3 2774.92   156.9 2770.91   168.8  2761.6   194.8 2760.36   217.3 2763.14
   237.4 2759.77     261  2766.5   303.1  2768.5   363.1 2763.48   414.4 2763.45
   430.1 2760.16   478.7 2763.62   492.5 2758.63   497.1 2757.98   518.3 2759.25
   518.9 2759.37   536.6 2764.08   583.9 2766.46   607.5 2770.75   706.1 2774.49
     777 2772.32   784.9 2775.71   800.5  2790.1   816.4 2799.83     930 2835.83
#Mann= 6 ,-1 , 0
       0      .1       0  171.63      .1       0  460.14      .1       0
   492.5    .045       0   518.3      .1       0   518.9      .1       0
#XS Ineff= 2 , 0
          473.68 2769.85
Permanent Ineff=
       F       F
Bank Sta=492.5,518.3
XS Rating Curve= 0 ,0
Exp/Cntr=0.3,0.1
LCMann Table=0

Chan Stop Cuts=-1
Use User Specified Reach Order=0
Composite Channel Slope=5